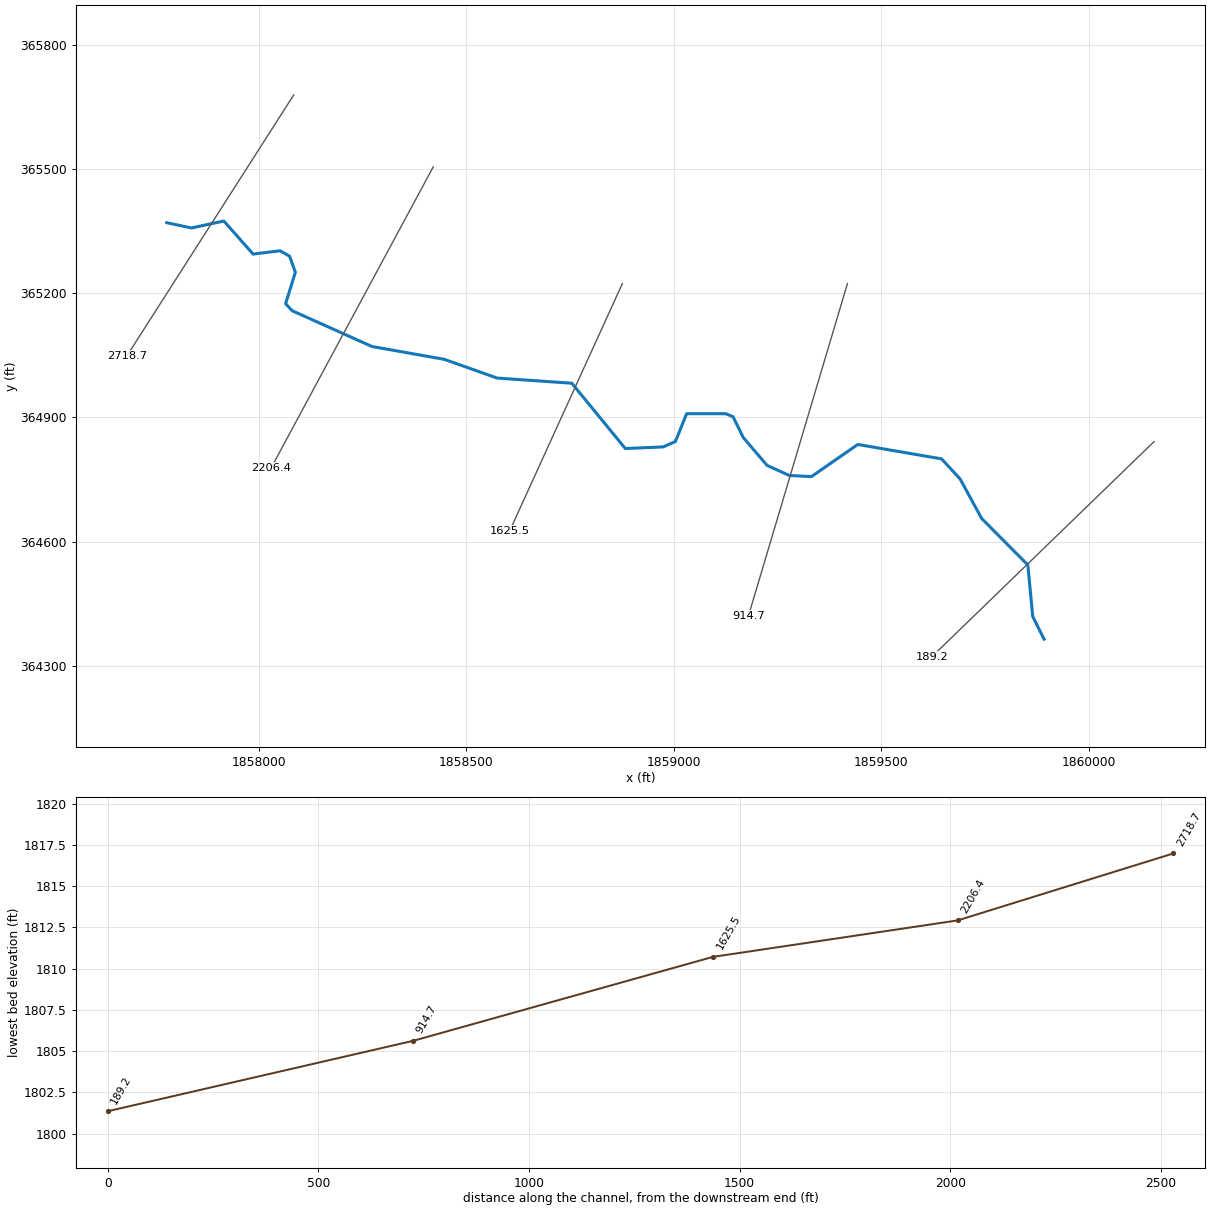
--- BoydRun.prj (project) ---

Proj Title=BoydRun
Current Plan=p01
Default Exp/Contr=0,0
English Units
Geom File=g01
Flow File=f01
Plan File=p01
BEGIN DESCRIPTION:
END DESCRIPTION:
DSS Export Rating Curves= 0
DSS Export Rating Curve Sorted= 0
DSS Export Volume Flow Curves= 0
DXF OffsetX= 0
DXF OffsetY= 0
DXF ScaleX= 0
DXF ScaleY= 0

--- BoydRun.p01 (plan) ---

Plan Title=Floodplain
Program Version=4.00
Geom File=g01
Flow File=f01
K Sum by GR=0
Std Step Tol=0.01
Critical Tol=0.01
Num of Std Step Trials=20
Max Error Tol=0.3
Flow Tol Ratio=0.001
Split Flow NTrial=30
Split Flow Tol=0.02
Split Flow Ratio=0.02
Log Output Level=0
Friction Slope Method=1
Unsteady Friction Slope Method=2
Unsteady Bridges Friction Slope Method=1
Global Log Level=0
CheckData=False
Run HTab=0
Run UNet=0
Run PostProcess=0
UNET Theta=0
UNET Theta Warmup=0
UNET ZTol=0
UNET ZSATol=0
UNET MxIter=0
UNET MaxInSteps=0
UNET DtIC=0
UNET DtMin=0
UNET MaxCRTS=0
UNET WFStab=0
UNET SFStab=0
UNET WFX=0
UNET SFX=0
UNET DSS MLevel=0
UNET DZMax Abort=0
UNET Convert EG Bridges=0
UNET Use Existing IB Tables=0
UNET Froude Limit=0
UNET Froude Power=0
Write IC File=0
Echo Input=False
Echo Output=False
Write Detailed=0

--- BoydRun.f01 (steady flow) ---

Flow Title=NFF Regression Equation
Program Version=4.10
Number of Profiles= 1
Profile Names=P100yr
River Rch & RM=BoydRun,Main            ,2718.7
     705
River Rch & RM=BoydRun,Main            ,189.2
     743
Boundary for River Rch & Prof#=BoydRun,Main            , 1
Up Type= 0
Dn Type= 3
Dn Slope=0.00588
DSS Import GetInterval= 0
DSS Import GetPeak= 0
DSS Import FillOption= 0

--- BoydRun.g01 (geometry) ---

Geom Title=USGS 10m DEM
Program Version=4.10

River Reach=BoydRun         ,Main
Reach XY= 30
     1857777.822      365370.349     1857837.392      365357.625
     1857915.469      365374.397     1857985.913      365294.585
     1858050.973      365302.532     1858073.983      365289.384
     1858087.789      365250.596      1858064.29       365174.84
     1858080.068      365157.748     1858272.258      365071.386
      1858446.56      365040.399     1858574.142      364995.126
     1858754.207      364982.635      1858883.06      364824.856
     1858974.375      364828.801     1859003.958      364841.949
     1859030.912      364909.005     1859124.922      364909.005
     1859142.672      364901.773     1859167.654      364851.153
     1859224.849      364784.097     1859278.494      364759.772
     1859331.744      364757.143     1859443.504      364834.717
     1859645.461      364799.875     1859690.165      364751.226
     1859742.101      364655.901     1859853.273      364543.643
     1859865.209       364418.86     1859892.335      364364.606

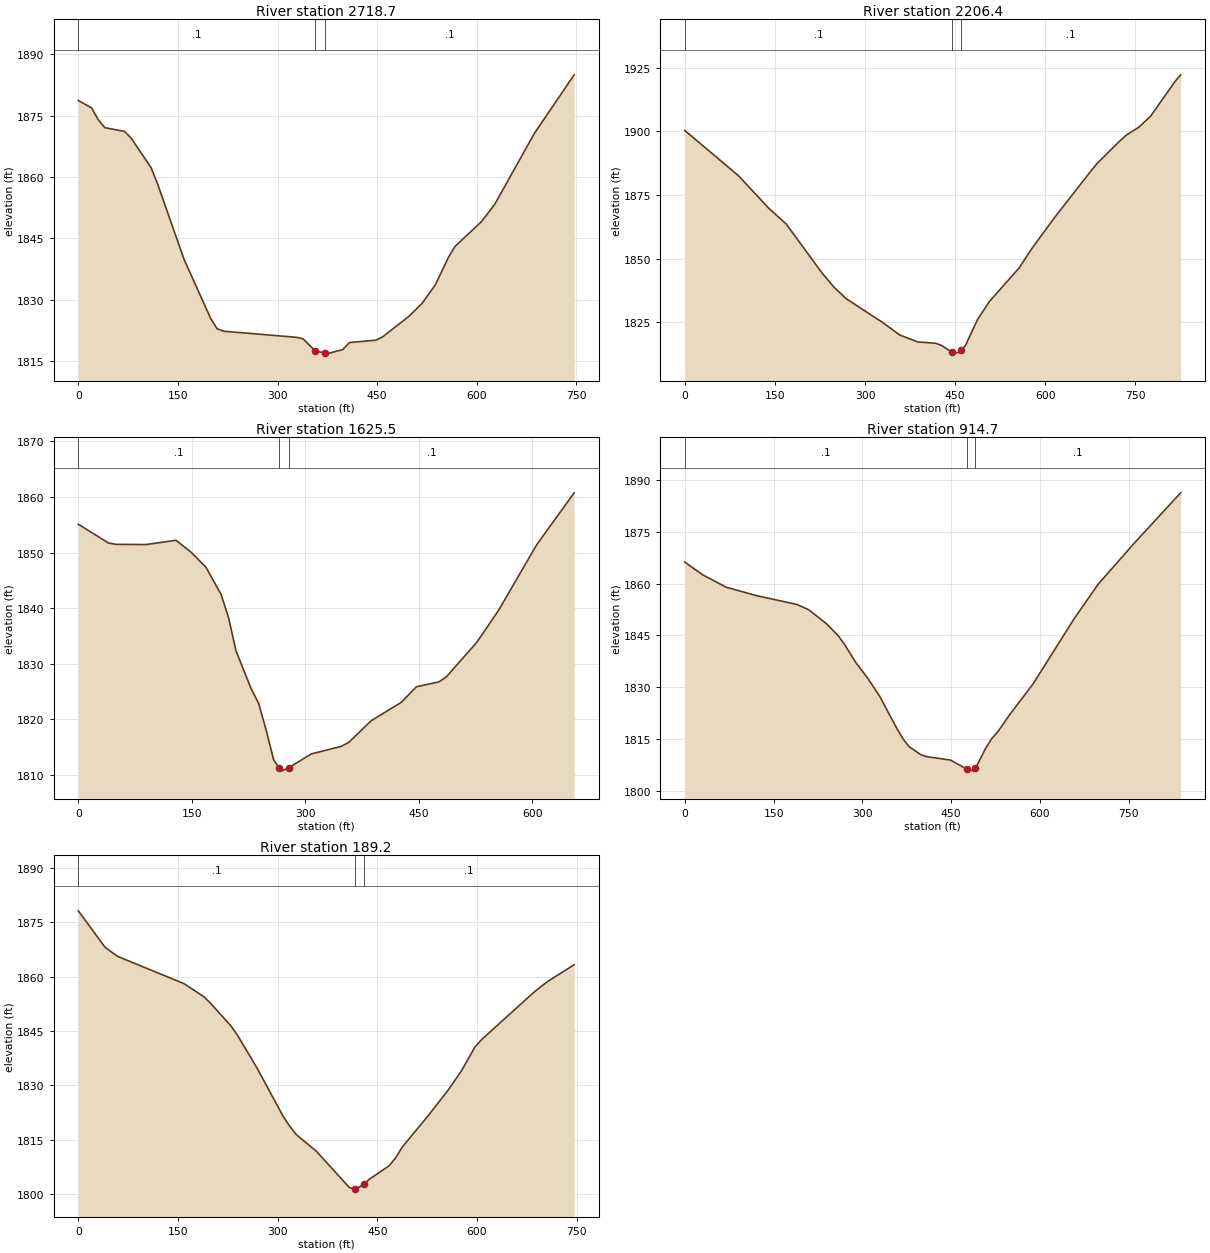
Type RM Length L Ch R = 1 ,2718.7  ,505.5,512.4,520.6
XS GIS Cut Line= 2
     1858083.804      365678.894     1857682.329      365049.553
#Sta/Elev= 30
       0 1878.67    19.9 1876.87    29.9 1874.01    39.8 1872.04    69.7 1871.12
    79.6 1869.47   109.5 1862.28   119.4 1858.27   159.2 1839.88   199.1  1825.5
     209 1822.93     219 1822.33   328.5 1820.84   338.4 1820.46   356.8  1817.5
   371.8    1817   378.2 1816.98   398.1 1817.85   408.1 1819.56   447.9 1820.14
   457.8 1820.91   497.7 1825.96   517.6 1829.15   537.5 1833.66   557.4 1840.44
   567.3 1843.06   607.2 1849.13     627 1853.35   686.8 1870.69   746.5 1884.94
#Mann= 3 , 0 , 0
       0      .1       0   356.8    .045       0   371.8      .1       0
Bank Sta=356.8,371.8
XS Rating Curve= 0 ,0
Exp/Cntr=0.3,0.1

Type RM Length L Ch R = 1 ,2206.4  ,579.4,580.9,582.5
XS GIS Cut Line= 2
     1858420.176      365505.283     1858029.551      364778.286
#Sta/Elev= 30
       0  1900.4    89.5 1882.58   139.2 1869.98     169  1863.6   228.7 1844.32
   248.6 1838.78   268.5 1834.32   328.1 1825.15     358 1820.01   387.8 1817.32
   417.6 1816.79   427.6 1815.91     445 1813.22   447.4 1812.92   457.4 1813.24
     460 1813.97   467.3 1816.01   487.2 1826.09   507.1 1833.23   556.8 1846.47
   576.7 1853.69   616.5 1866.52   676.2 1884.53   686.1 1887.39   725.9 1896.69
   735.8 1898.72   755.7 1901.67   775.6  1906.1   815.4 1919.46   825.3 1922.26
#Mann= 3 , 0 , 0
       0      .1       0     445    .045       0     460      .1       0
Bank Sta=445,460
XS Rating Curve= 0 ,0
Exp/Cntr=0.3,0.1

Type RM Length L Ch R = 1 ,1625.5  ,708,710.8,711.8
XS GIS Cut Line= 2
     1858875.905      365223.165     1858604.638      364626.376
#Sta/Elev= 30
       0  1855.1    39.7 1851.73    49.7 1851.48    89.4 1851.44   129.1 1852.21
     149 1850.08   168.8 1847.35   188.7  1842.5   198.6 1838.32   208.6 1832.28
   228.4 1825.56   238.4  1822.9   248.3 1818.11   258.2 1812.78   265.8 1811.21
   268.2 1810.71   278.1  1811.3   307.9  1813.8   347.6 1815.16   357.6 1815.88
   387.4 1819.79   427.1 1823.08     447 1825.88   476.8 1826.75   486.7 1827.67
   526.4  1833.8   536.4 1835.75   556.2 1839.74   605.9 1851.37   655.6 1860.74
#Mann= 3 , 0 , 0
       0      .1       0   265.8    .045       0   278.1      .1       0
Bank Sta=265.8,278.1
XS Rating Curve= 0 ,0
Exp/Cntr=0.3,0.1

Type RM Length L Ch R = 1 ,914.7   ,737,725.5,713.9
XS GIS Cut Line= 2
      1859418.44      365223.165     1859179.724      364420.213
#Sta/Elev= 30
       0 1866.29    29.9 1862.62    69.8 1859.01   119.7 1856.61   189.5 1853.99
   209.4 1852.46   239.3  1848.4   259.3  1844.9   269.3 1842.55   289.2  1837.1
   309.2 1832.54   329.1 1827.42     359 1817.76     369 1814.94     379 1812.73
   398.9 1810.39   408.9 1809.81   448.8 1808.84     476 1806.28   488.6 1805.63
     491  1806.4   508.6 1812.37   518.6 1815.07   528.5 1816.97   548.5 1821.92
   588.4 1830.94   658.2 1849.95   698.1  1859.8   757.9  1871.5   837.7 1886.38
#Mann= 3 , 0 , 0
       0      .1       0     476    .045       0     491      .1       0
Bank Sta=476,491
XS Rating Curve= 0 ,0
Exp/Cntr=0.3,0.1

Type RM Length L Ch R = 1 ,189.2   ,194.4,189.2,183.1
XS GIS Cut Line= 2
     1860157.589      364841.654     1859621.936       364321.97
#Sta/Elev= 30
       0 1878.12    39.8 1868.17    49.8 1866.77    59.7 1865.51   159.2 1858.03
   189.1 1854.41     199 1852.62   228.9 1846.57   238.8 1844.02   268.7 1834.85
   308.5 1821.37   318.4 1818.65   328.4 1816.34   358.2 1811.82     408 1801.79
   416.4 1801.42   417.9 1801.36  430.29 1802.77   437.8 1804.07   467.7 1807.79
   477.6 1809.99   487.6 1812.98   527.4  1821.8   557.2 1828.82   577.2 1834.15
   597.1 1840.59     607 1842.61   686.6 1855.81   706.5 1858.65   746.3 1863.26
#Mann= 3 , 0 , 0
       0      .1       0   416.4    .045       0  430.29      .1       0
Bank Sta=416.4,430.29
XS Rating Curve= 0 ,0
Exp/Cntr=0.3,0.1

Chan Stop Cuts=-1
Use User Specified Reach Order=0
Composite Channel Slope=5